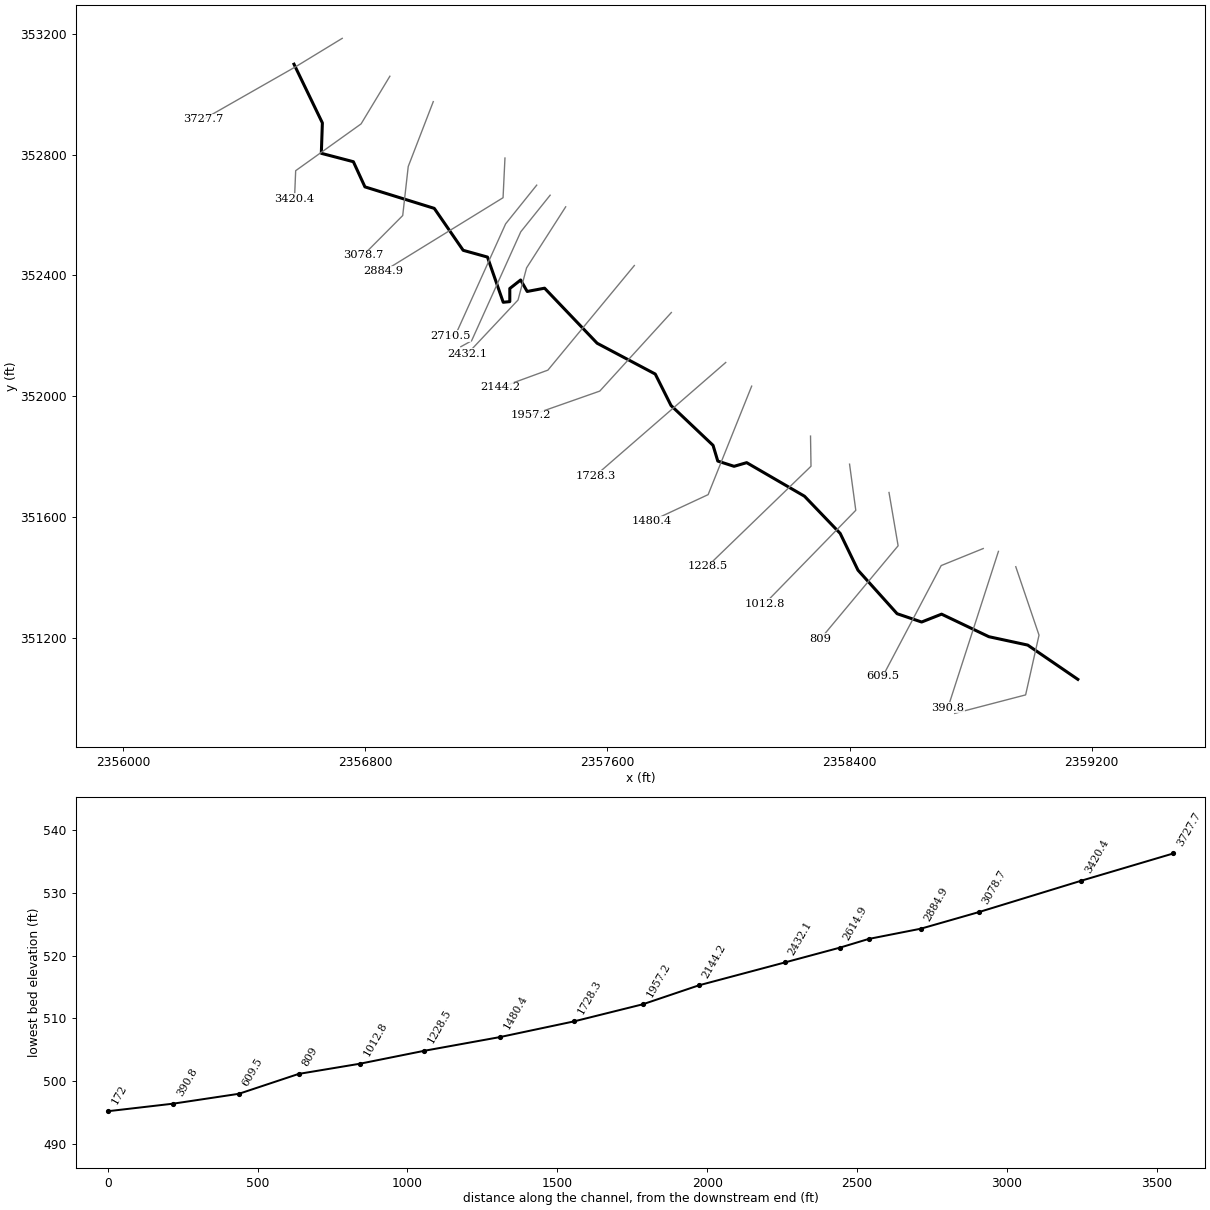
--- ELKBRTRIB2.prj (project) ---

Proj Title=ELKBRTRIB2
Current Plan=p01
Default Exp/Contr=0,0
English Units
Geom File=g01
Flow File=f01
Plan File=p01
BEGIN DESCRIPTION:
END DESCRIPTION:
DSS Export Rating Curves= 0
DSS Export Rating Curve Sorted= 0
DSS Export Volume Flow Curves= 0
DXF OffsetX= 0
DXF OffsetY= 0
DXF ScaleX= 0
DXF ScaleY= 0

--- ELKBRTRIB2.p01 (plan) ---

Plan Title=Floodplain
Program Version=4.00
Geom File=g01
Flow File=f01
K Sum by GR=0
Std Step Tol=0.01
Critical Tol=0.01
Num of Std Step Trials=20
Max Error Tol=0.3
Flow Tol Ratio=0.001
Split Flow NTrial=30
Split Flow Tol=0.02
Split Flow Ratio=0.02
Log Output Level=0
Friction Slope Method=1
Unsteady Friction Slope Method=2
Unsteady Bridges Friction Slope Method=1
Global Log Level=0
CheckData=False
Run HTab=0
Run UNet=0
Run PostProcess=0
UNET Theta=0
UNET Theta Warmup=0
UNET ZTol=0
UNET ZSATol=0
UNET MxIter=0
UNET MaxInSteps=0
UNET DtIC=0
UNET DtMin=0
UNET MaxCRTS=0
UNET WFStab=0
UNET SFStab=0
UNET WFX=0
UNET SFX=0
UNET DSS MLevel=0
UNET DZMax Abort=0
UNET Convert EG Bridges=0
UNET Use Existing IB Tables=0
UNET Froude Limit=0
UNET Froude Power=0
Write IC File=0
Echo Input=False
Echo Output=False
Write Detailed=0

--- ELKBRTRIB2.f01 (steady flow) ---

Flow Title=NFF Regression Equation
Program Version=5.03
Number of Profiles= 1
Profile Names=P100yr
River Rch & RM=ELKBRTRIB2,Main            ,3727.7
572.2177
River Rch & RM=ELKBRTRIB2,Main            ,809
605.4357
River Rch & RM=ELKBRTRIB2,Main            ,390.8
 641.589
Boundary for River Rch & Prof#=ELKBRTRIB2,Main            , 1
Up Type= 0
Dn Type= 3
Dn Slope=0.00472
DSS Import GetInterval= 0
DSS Import GetPeak= 0
DSS Import FillOption= 0

--- ELKBRTRIB2.g01 (geometry) ---

Geom Title=USGS 10m DEM
Program Version=5.03

River Reach=ELKBRTRIB2      ,Main
Reach XY= 30
     2356564.112      353099.565     2356657.861      352905.121
     2356654.389      352804.427     2356760.292      352776.649
     2356798.486      352693.316     2357027.653      352622.135
     2357123.139      352483.246     2357203.434      352460.893
     2357255.518      352311.154     2357277.219      352313.324
     2357277.219      352356.727     2357313.026      352384.939
     2357334.728      352346.961     2357392.237      352357.812
     2357565.847       352175.52     2357757.977      352073.451
      2357810.06      351969.285     2357948.949       351837.34
     2357964.574      351785.257     2358018.394      351767.896
      2358060.06      351780.049     2358251.033      351668.938
     2358369.088      351545.674     2358427.857      351424.022
     2358557.192        351279.8     2358638.185      351252.271
     2358704.158      351278.313     2358860.408       351203.66
      2358988.88      351175.882     2359154.444      351062.377

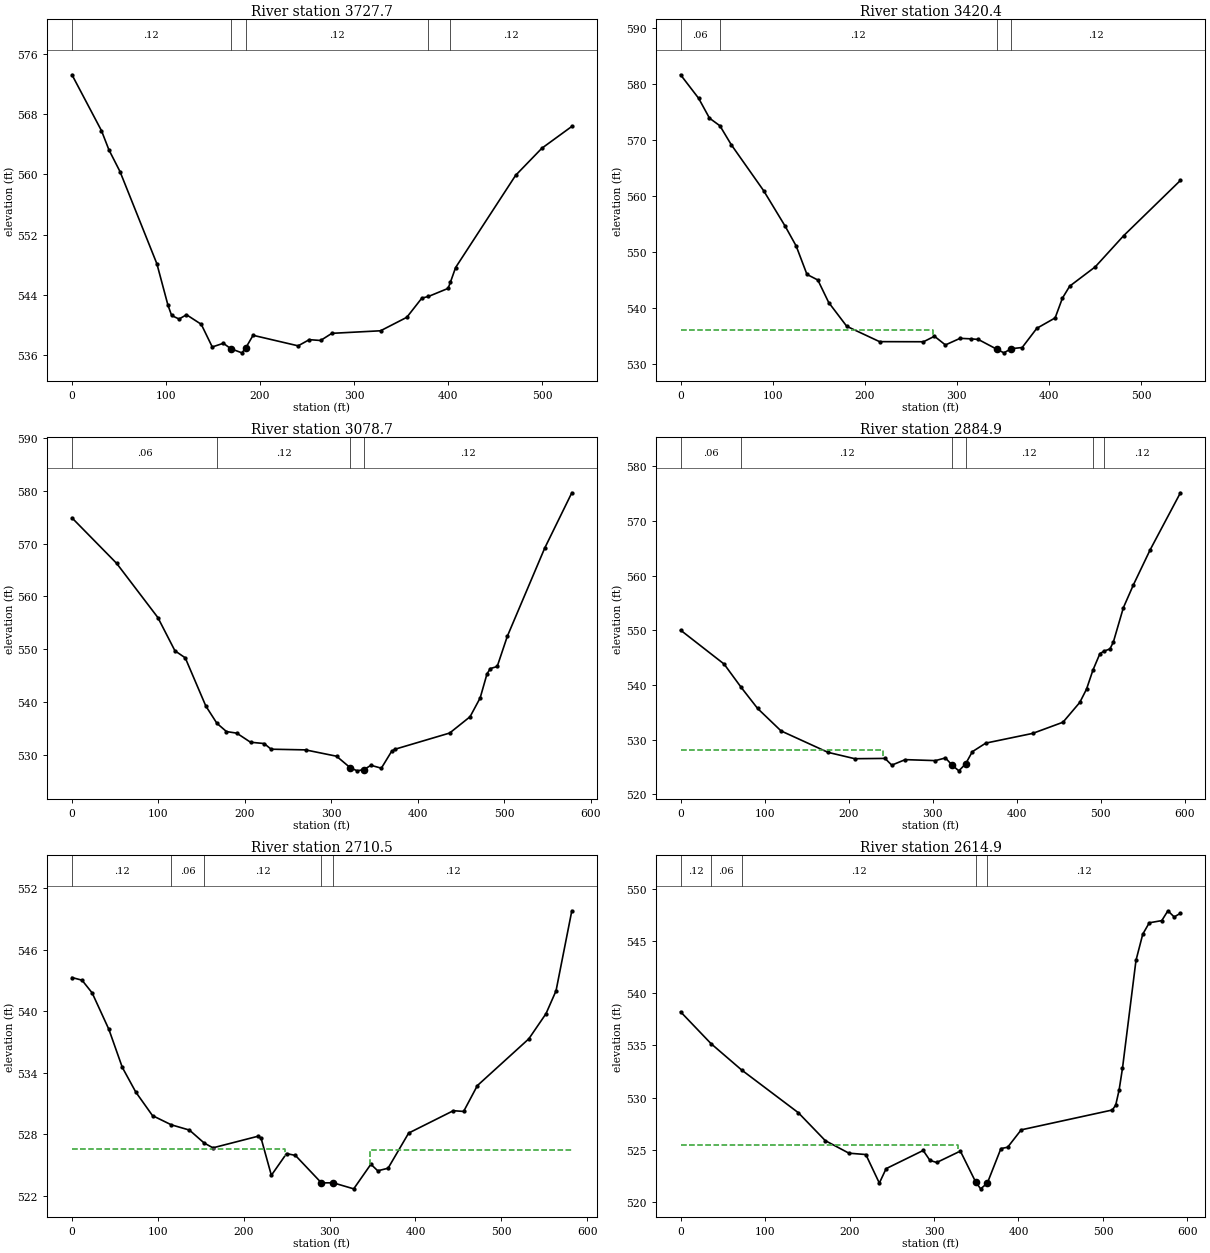
Type RM Length L Ch R = 1 ,3727.7  ,305.6,307.3,309.7
XS GIS Cut Line= 3
     2356723.482      353185.238     2356569.326      353091.033
     2356264.597      352916.943
#Sta/Elev= 30
       0  573.24    31.4  565.81    39.3  563.27    51.1  560.38    90.3  548.14
   102.1  542.63     106  541.27   113.9   540.8   121.8  541.37   137.5   540.1
   149.2  537.09     161  537.58   168.9  536.86   180.7  536.31   184.6  536.92
   192.6  538.64   240.5  537.24   252.4  538.06   264.4  537.95   276.4   538.9
   328.2  539.24   356.1  541.03   372.1  543.58  379.14543.7976     400  544.87
  402.49545.6917     408  547.64   471.8  559.88   499.7  563.48   531.6  566.38
#Mann= 5 ,-1 , 0
       0     .12       0   168.9    .045       0   184.6     .12       0
  379.14     .06       0  402.49     .12       0
Bank Sta=168.9,184.6
XS Rating Curve= 0 ,0
Exp/Cntr=0.3,0.1

Type RM Length L Ch R = 1 ,3420.4  ,322.3,341.6,360.6
XS GIS Cut Line= 4
     2356880.899       353059.72     2356785.787      352901.889
     2356569.641      352746.941     2356565.794       352654.61
#Sta/Elev= 30
       0  581.63    19.6  577.43    31.4  573.88   42.73572.5155    54.9  569.17
    90.2  560.92   113.7  554.54   125.5  551.04   137.2  545.97     149  544.97
   160.8  540.95   180.4   536.7     216  533.96   263.7  533.94   275.6  534.92
   287.5  533.37   303.4  534.55   315.3  534.46   323.2  534.35     343  532.63
     351  531.96   358.9   532.7   370.8  532.91   386.7  536.34   406.6   538.2
   414.5  541.73   422.4  543.87   450.2  547.33     481  552.89   542.6  562.76
#Mann= 4 ,-1 , 0
       0     .06       0   42.73     .12       0     343    .045       0
   358.9     .12       0
#XS Ineff= 2 , 0
           274.3  535.98
Permanent Ineff=
       F       F
Bank Sta=343,358.9
XS Rating Curve= 0 ,0
Exp/Cntr=0.3,0.1

Type RM Length L Ch R = 1 ,3078.7  ,214.3,193.8,173
XS GIS Cut Line= 4
     2357024.338      352975.636     2356941.592      352760.732
     2356923.363      352598.406     2356793.463      352467.391
#Sta/Elev= 30
       0  574.89    51.6  566.28    99.3  556.01   119.1   549.7     131  548.37
   154.8  539.24  167.63535.9638   178.7   534.4   190.6   534.1   206.5  532.38
   222.3  532.13   230.3  531.06   270.1  530.93     306  529.73   321.9  527.54
   329.9  526.96   337.8  527.21   345.8  528.01   357.8  527.46   369.7  530.66
   373.7  531.06   436.8  534.12   460.4  537.21   472.1  540.78     480  545.33
   483.9  546.34   491.8  546.73   503.5  552.45   546.7  569.14   578.1  579.64
#Mann= 4 ,-1 , 0
       0     .06       0  167.63     .12       0   321.9    .045       0
   337.8     .12       0
Bank Sta=321.9,337.8
XS Rating Curve= 0 ,0
Exp/Cntr=0.3,0.1

Type RM Length L Ch R = 1 ,2884.9  ,159.9,174.5,211.3
XS GIS Cut Line= 3
     2357261.252      352788.812      2357254.96      352657.434
     2356860.567      352413.956
#Sta/Elev= 30
       0  550.04    51.8  543.84   72.23539.5554    91.7  535.72   119.6  531.61
   175.5  527.69   207.4  526.53   243.4  526.58   251.4  525.35   267.4  526.36
   303.3  526.18   315.3  526.67   323.3  525.34   331.3  524.31   339.3  525.59
   347.3  527.81   363.3  529.38   419.2  531.16   455.2   533.2   475.2  536.82
   483.2  539.24  490.88542.7361   499.1  545.72  503.58546.1664   511.1  546.61
   515.1  547.83   527.1  554.15   539.1  558.35   559.1  564.77     595  575.16
#Mann= 6 ,-1 , 0
       0     .06       0   72.23     .12       0   323.3    .045       0
   339.3     .12       0  490.88     .06       0  503.58     .12       0
#XS Ineff= 2 , 0
          240.87  528.11
Permanent Ineff=
       F       F
Bank Sta=323.3,339.3
XS Rating Curve= 0 ,0
Exp/Cntr=0.3,0.1

Type RM Length L Ch R = 1 ,2710.5  ,94.2,95.5,76.3
XS GIS Cut Line= 4
     2357366.122       352699.06     2357263.467      352570.889
     2357100.982      352209.973     2357081.592      352199.417
#Sta/Elev= 30
       0  543.28    11.7  543.02    23.5  541.78      43  538.22    58.6  534.52
    74.3  532.11    93.8  529.81  115.61528.9174   136.8   528.4  153.93527.1383
   164.2  526.67   216.2  527.79   220.2  527.62   232.2  523.99  249.88  526.11
   260.2  525.93  290.49523.2498   304.1  523.26   328.1  522.67   348.1  525.07
   356.1  524.43   368.1  524.68   392.1  528.11   444.1  530.29   456.1  530.22
   472.1  532.74     532   537.3     552  539.75   563.7  541.98   582.1  549.79
#Mann= 5 ,-1 , 0
       0     .12       0  115.61     .06       0  153.93     .12       0
  290.49    .045       0   304.1     .12       0
#XS Ineff= 2 , 0
           248.3  526.54  347.37          526.44
Permanent Ineff=
       F       F
Bank Sta=290.49,304.1
XS Rating Curve= 0 ,0
Exp/Cntr=0.3,0.1

Type RM Length L Ch R = 1 ,2614.9  ,123.2,182.8,185.8
XS GIS Cut Line= 4
     2357410.562       352665.73     2357313.467        352544.5
     2357150.982      352183.584     2357115.446      352164.051
#Sta/Elev= 30
       0  538.22   36.15535.1672   72.26532.6582   139.4  528.57   171.3   525.9
   199.3   524.7   219.3  524.57   235.3  521.84   243.3  523.22   287.2  524.96
   295.2  524.01   303.2  523.81   331.2   524.9  349.39521.9362   355.2  521.29
   363.1  521.83   379.2  525.14   387.2  525.27   403.2  526.93   511.1  528.83
   515.1   529.3   519.1  530.73   523.1  532.81   539.1  543.14   547.1  545.64
   554.8  546.73   569.6  546.94   576.9  547.88   584.3  547.29   591.7  547.64
#Mann= 5 ,-1 , 0
       0     .12       0   36.15     .06       0   72.26     .12       0
  349.39    .045       0   363.1     .12       0
#XS Ineff= 2 , 0
          328.79  525.47
Permanent Ineff=
       F       F
Bank Sta=349.39,363.1
XS Rating Curve= 0 ,0
Exp/Cntr=0.3,0.1

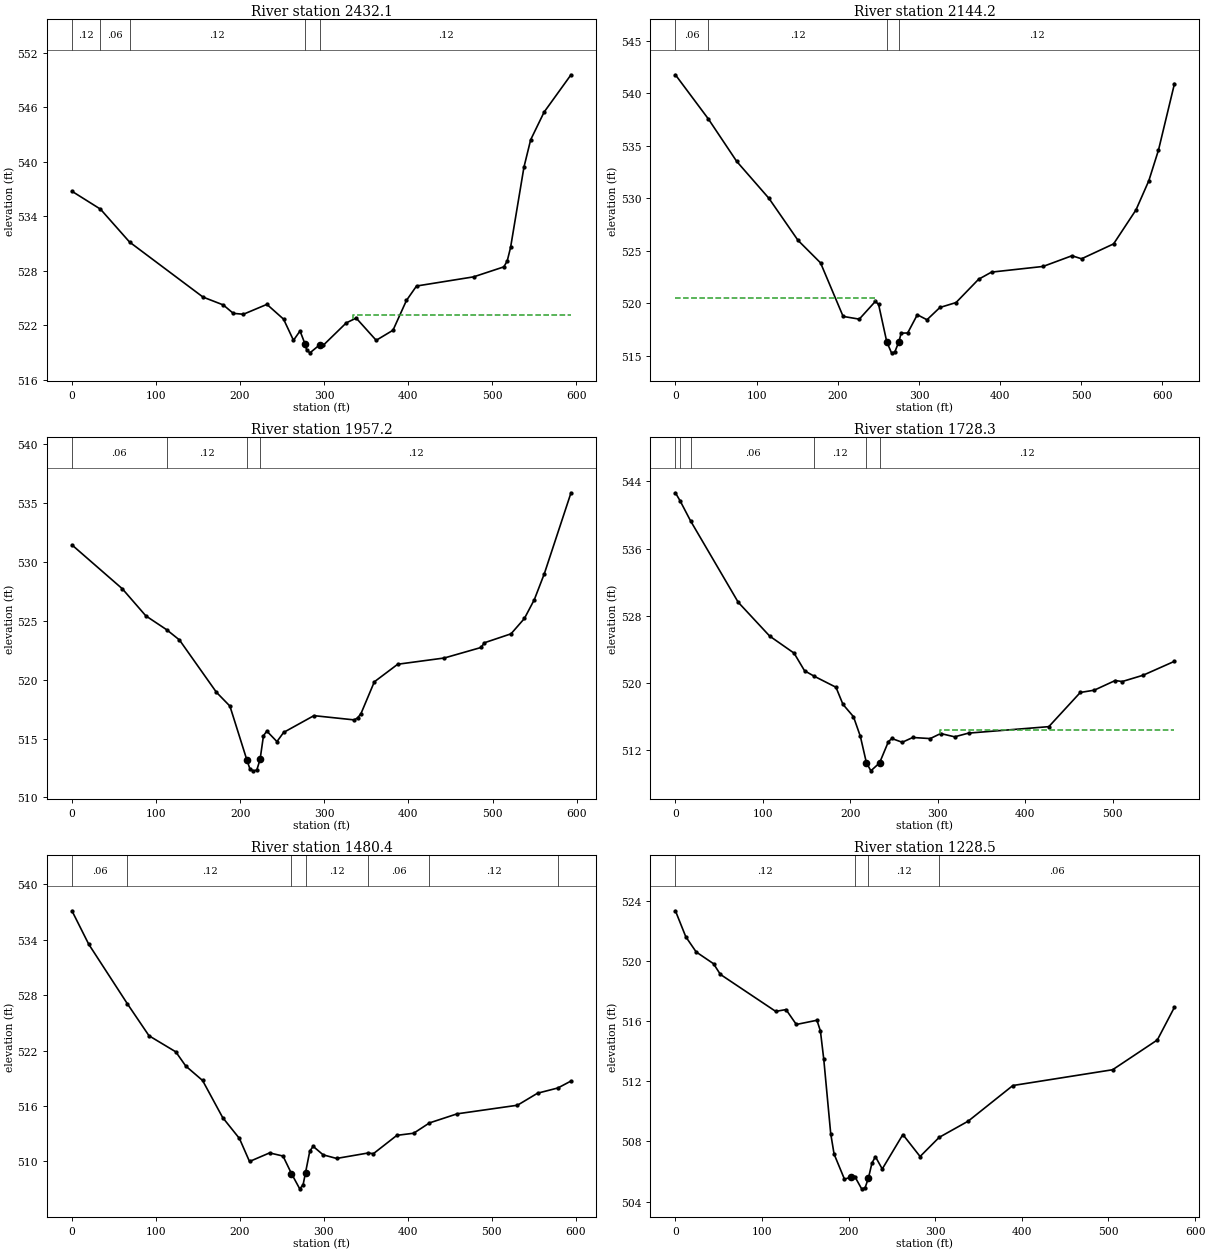
Type RM Length L Ch R = 1 ,2432.1  ,291.9,287.9,267.1
XS GIS Cut Line= 4
     2357461.916      352627.214     2357332.651      352425.012
     2357304.439      352318.675     2357137.649      352140.857
#Sta/Elev= 30
       0  536.74   33.95534.7676   68.62531.1396     156  525.08     180  524.22
     192  523.29     204  523.19     232  524.28   251.8  522.65   263.6  520.32
   271.4  521.35   277.3519.9211   279.3  519.26   283.2  518.94     295  519.84
   298.9  519.76   326.4  522.24   338.2  522.77     362  520.32     382  521.43
     398  524.71     410   526.3   477.9  527.31   513.9  528.41   517.9  529.06
   521.9  530.55   537.8  539.39   545.8  542.41   561.8  545.46   593.8  549.57
#Mann= 5 ,-1 , 0
       0     .12       0   33.95     .06       0   68.62     .12       0
   277.3    .045       0     295     .12       0
#XS Ineff= 2 , 0
                          334.98          523.16
Permanent Ineff=
       F       F
Bank Sta=277.3,295
XS Rating Curve= 0 ,0
Exp/Cntr=0.3,0.1

Type RM Length L Ch R = 1 ,2144.2  ,188.7,187,185.9
XS GIS Cut Line= 3
      2357688.83      352432.841     2357403.181       352086.47
      2357247.44      352029.405
#Sta/Elev= 30
       0  541.77   40.49 537.573    75.5  533.52   115.2     530     151     526
   178.8  523.85   206.6  518.75   226.5  518.49   246.3  520.18   250.3  519.89
   260.4  516.32   266.2  515.28   270.2  515.35   275.4  516.36   278.1  517.16
   286.1  517.17     298  518.91   309.9  518.43   325.8   519.6   345.7  520.07
   373.5  522.29   389.4  522.97   452.9  523.51   488.5  524.53   500.3  524.24
   539.8  525.66   567.4   528.9   583.2  531.68   595.1   534.6   614.8  540.93
#Mann= 4 ,-1 , 0
       0     .06       0   40.49     .12       0   260.4    .045       0
   275.4     .12       0
#XS Ineff= 2 , 0
          246.34  520.52
Permanent Ineff=
       F       F
Bank Sta=260.4,275.4
XS Rating Curve= 0 ,0
Exp/Cntr=0.3,0.1

Type RM Length L Ch R = 1 ,1957.2  ,230.9,228.9,226
XS GIS Cut Line= 3
     2357811.131      352277.186     2357574.622      352017.026
     2357346.593      351936.766
#Sta/Elev= 30
       0  531.42    59.9   527.7    87.9   525.4  112.65 524.225   127.8  523.36
   171.8  518.92   187.8  517.75   207.8  513.22   211.8  512.38   215.8  512.26
   219.8  512.33   223.7  513.24   227.7  515.24   231.7  515.63   243.7  514.74
   251.7  515.52   287.7  516.94   335.6  516.58   339.6  516.75   343.6  517.11
   359.5  519.81   387.3   521.3   442.7  521.83   486.3  522.72   490.3  523.12
     522  523.88   537.9  525.18   549.7  526.78   561.6  528.98   593.3  535.84
#Mann= 4 ,-1 , 0
       0     .06       0  112.65     .12       0   207.8    .045       0
   223.7     .12       0
Bank Sta=207.8,223.7
XS Rating Curve= 0 ,0
Exp/Cntr=0.3,0.1

Type RM Length L Ch R = 1 ,1728.3  ,236.7,247.9,258.8
XS GIS Cut Line= 2
     2357990.828      352111.774     2357560.359      351737.043
#Sta/Elev= 30
       0  542.64    5.38541.6778    17.3   539.3    71.8  529.61   107.8  525.58
   135.7  523.55   147.7  521.45  158.73520.8018   183.6  519.49   191.6  517.45
   203.6  515.99   211.5  513.64  218.34510.5327   223.5  509.54  233.43510.4836
   243.5     513   247.4  513.39   259.4  512.94   271.4  513.51   291.4  513.38
   303.3  513.98   319.3  513.59   335.2  514.03     427   514.8     463  518.87
   478.9  519.14   502.9  520.29   510.9  520.17   534.8  520.92   570.7  522.58
#Mann= 6 ,-1 , 0
       0     .06       0    5.38     .08       0    17.3     .06       0
  158.73     .12       0  218.34    .045       0  233.43     .12       0
#XS Ineff= 2 , 0
                          302.79          514.46
Permanent Ineff=
       F       F
Bank Sta=218.34,233.43
XS Rating Curve= 0 ,0
Exp/Cntr=0.3,0.1

Type RM Length L Ch R = 1 ,1480.4  ,261.6,251.9,242.4
XS GIS Cut Line= 3
     2358076.568      352033.416     2357932.695      351674.144
     2357744.743      351586.493
#Sta/Elev= 30
       0  537.13      20  533.51   66.13 527.048    91.8   523.6   123.7  521.86
   135.6  520.32   155.6  518.76   179.5  514.75   199.5  512.48   211.5  509.99
   235.4  510.92   251.4  510.58  261.48508.6803   271.3  507.03   275.3  507.46
  278.23508.7932   283.3  511.12   287.3  511.63   299.2  510.71   315.2  510.32
  352.65 510.909   359.1  510.84     387  512.82     407  513.05  425.85514.1669
   458.8  515.15   530.6  516.08   554.5  517.38  578.77517.9494   594.4   518.7
#Mann= 7 ,-1 , 0
       0     .06       0   66.13     .12       0  261.48    .045       0
  278.23     .12       0  352.65     .06       0  425.85     .12       0
  578.77     .06       0
Bank Sta=261.48,278.23
XS Rating Curve= 0 ,0
Exp/Cntr=0.3,0.1

Type RM Length L Ch R = 1 ,1228.5  ,215.1,215.7,216.3
XS GIS Cut Line= 3
     2358271.054      351867.965      2358272.64      351768.089
     2357930.553      351436.646
#Sta/Elev= 30
       0  523.34      12  521.61      24   520.6      44  519.82    51.9  519.11
   115.8  516.65   127.7  516.77   139.6  515.78   163.4  516.06   167.4  515.35
   171.3  513.46   179.3  508.52   183.2  507.16   195.2  505.49   203.1  505.64
   207.1  505.67     215  504.85     219  504.92   222.9  505.58   226.9  506.56
   230.9  506.99   238.8  506.17   262.6  508.46   282.5     507  304.48508.2708
     338  509.35   389.6  511.72   504.8  512.77   556.4  514.75   576.2  516.93
#Mann= 4 ,-1 , 0
       0     .12       0   207.1    .045       0   222.9     .12       0
  304.48     .06       0
Bank Sta=203.1,222.9
XS Rating Curve= 0 ,0
Exp/Cntr=0.3,0.1

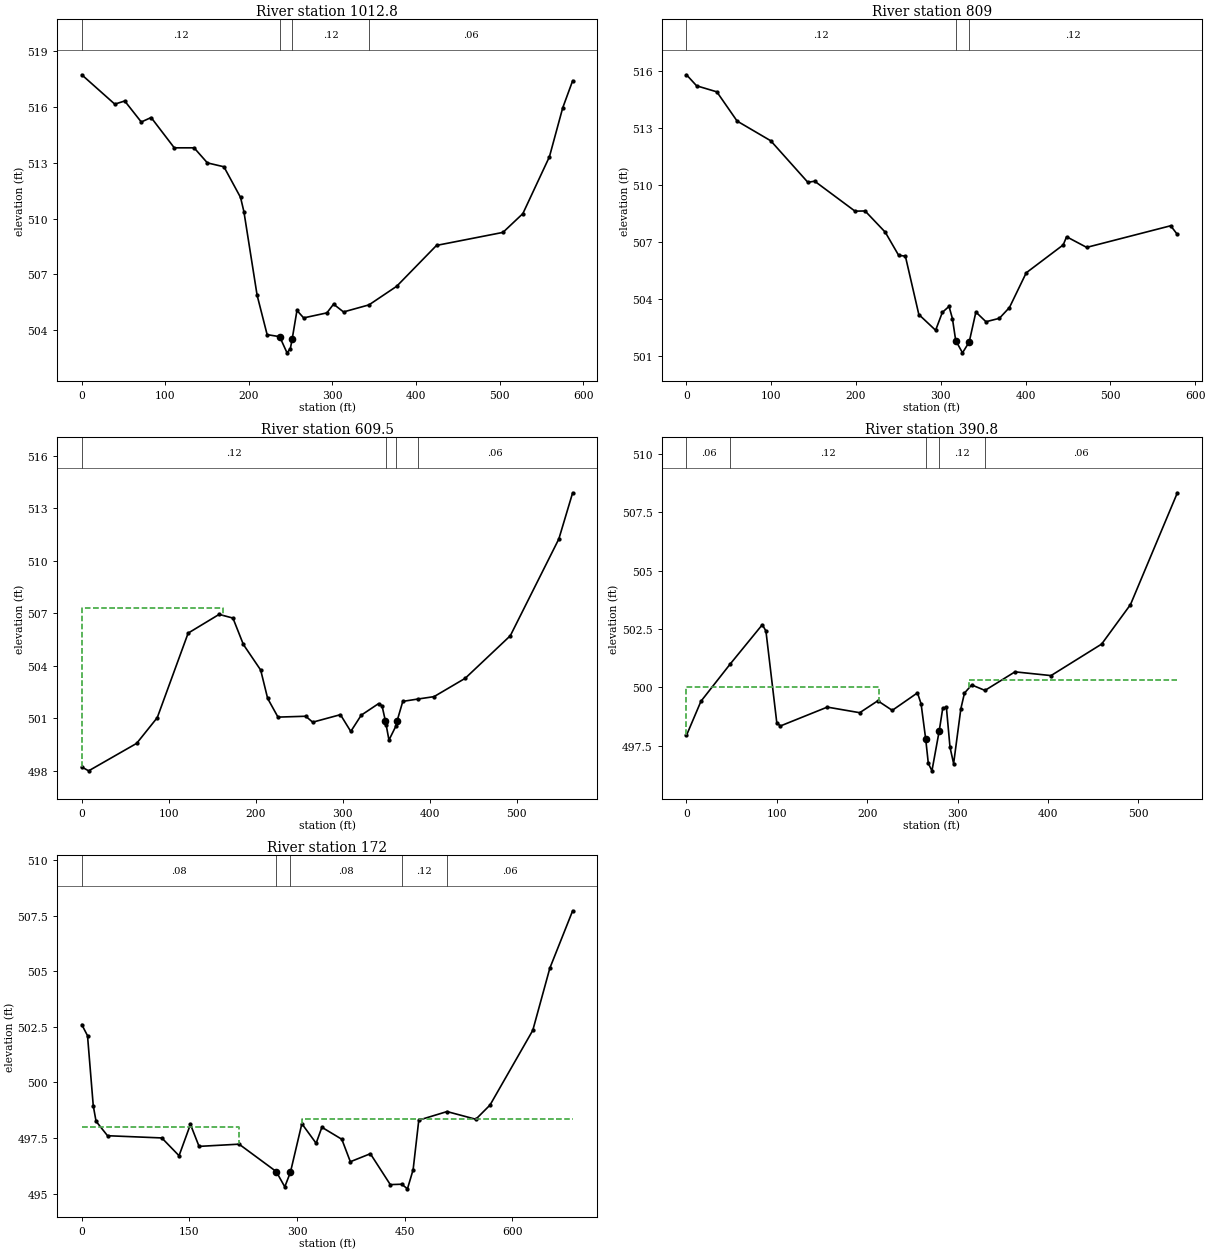
Type RM Length L Ch R = 1 ,1012.8  ,202,203.8,205.7
XS GIS Cut Line= 3
     2358400.055      351775.085     2358420.643      351622.256
     2358118.572      351311.735
#Sta/Elev= 30
       0  517.74    39.5  516.16    51.4  516.33    71.2   515.2      83  515.44
   110.7  513.81   134.4  513.81   150.3     513   170.1  512.79     190  511.14
     194  510.38   209.8  505.88   221.8  503.76   236.8  503.65   245.6  502.78
   249.6  503.01   251.8  503.53   257.5  505.06   265.5  504.66   293.3  504.93
   301.3   505.4   313.2  504.98  343.68505.3602   376.8  506.36   424.5  508.56
     504  509.26   527.8  510.27   559.6  513.33   575.5  515.96   587.4  517.42
#Mann= 4 ,-1 , 0
       0     .12       0   236.8    .045       0   251.8     .12       0
  343.68     .06       0
Bank Sta=236.8,251.8
XS Rating Curve= 0 ,0
Exp/Cntr=0.3,0.1

Type RM Length L Ch R = 1 ,809     ,194.6,199.5,204.2
XS GIS Cut Line= 3
     2358530.444      351681.205     2358560.527      351504.754
     2358304.695      351197.135
#Sta/Elev= 30
       0  515.82    11.9  515.24    35.8  514.92    59.7  513.38    99.4  512.34
   143.2  510.15   151.2  510.21   198.8  508.63   210.7  508.64   234.5  507.52
   250.3   506.3   258.2  506.26   274.1  503.18   293.9  502.35   301.8  503.29
   309.7  503.61   313.7  502.97   317.6  501.81   325.6  501.16   333.5  501.73
   341.4  503.31   353.3   502.8   369.1  502.98     381  503.55   400.8  505.38
   444.4  506.85   448.4  507.28   472.1  506.72   571.2  507.86   579.1   507.4
#Mann= 3 ,-1 , 0
       0     .12       0   317.6    .045       0   333.5     .12       0
Bank Sta=317.6,333.5
XS Rating Curve= 0 ,0
Exp/Cntr=0.3,0.1

Type RM Length L Ch R = 1 ,609.5   ,214.3,218.7,222.7
XS GIS Cut Line= 3
     2358841.777      351495.639     2358702.888      351439.215
     2358509.745      351072.462
#Sta/Elev= 30
       0  498.21     7.9  497.99    63.1  499.56    86.8  501.03   122.3  505.86
   157.9  506.93   173.8  506.72   185.8  505.21   205.7  503.75   213.7  502.13
   225.6  501.06   257.5  501.11   265.5  500.77   297.4   501.2   309.3  500.24
   321.3  501.17   341.2  501.83   345.2  501.71   349.2  500.82  350.03 500.598
   353.2  499.75   361.2  500.55  362.59  500.85   369.1  501.96  386.62502.0945
     405  502.23   440.9  503.28   492.7  505.71   548.5  511.24   564.4  513.88
#Mann= 4 ,-1 , 0
       0     .12       0  350.03    .045       0   361.2     .12       0
  386.62     .06       0
#XS Ineff= 2 , 0
          162.85  507.31
Permanent Ineff=
       F       F
Bank Sta=349.2,362.59
XS Rating Curve= 0 ,0
Exp/Cntr=0.3,0.1

Type RM Length L Ch R = 1 ,390.8   ,216.7,218.8,220.9
XS GIS Cut Line= 2
     2358892.054      351486.186     2358725.291      350969.186
#Sta/Elev= 30
       0  497.94      16   499.4   48.58501.0057    83.9  502.68    87.9  502.41
    99.9  498.49   103.8  498.34   155.8  499.15   191.7  498.91   211.7  499.42
   227.7  499.01   255.6  499.76   259.6  499.29   264.7  497.78   267.6  496.74
   271.6  496.42   279.7  498.14   283.6  499.11   287.6  499.14   291.6  497.43
   295.6  496.73   303.6  499.08   307.6  499.75   315.6   500.1  330.29499.8649
   363.5  500.66   403.4   500.5   459.4  501.85   491.3  503.54   543.2  508.33
#Mann= 5 ,-1 , 0
       0     .06       0   48.58     .12       0   264.7    .045       0
   279.7     .12       0  330.29     .06       0
#XS Ineff= 2 , 0
             213  500.02  312.69          500.33
Permanent Ineff=
       F       F
Bank Sta=264.7,279.7
XS Rating Curve= 0 ,0
Exp/Cntr=0.3,0.1

Type RM Length L Ch R = 1 ,172     ,182.9,172,161
XS GIS Cut Line= 4
     2358949.345      351435.405     2359026.168      351208.842
     2358981.897      351010.926     2358747.522      350949.728
#Sta/Elev= 30
       0   502.6       8   502.1      16  498.95    19.9  498.25    35.9   497.6
   111.6   497.5   135.6   496.7   151.5  498.11   163.5  497.12   219.3  497.22
     271  495.99     283   495.3   290.9  495.96   306.8  498.14   326.7  497.26
   334.7  497.98   362.5  497.44   374.4  496.43   402.3  496.79   430.1   495.4
  446.08495.4176     454  495.21   461.9  496.07   469.8   498.3  509.18498.6864
   549.3  498.34   569.1  498.98   628.7  502.34   652.5  505.14   684.3  507.72
#Mann= 5 ,-1 , 0
       0     .08       0     271    .045       0   290.9     .08       0
  446.08     .12       0  509.18     .06       0
#XS Ineff= 2 , 0
          218.89     498  307.02          498.33
Permanent Ineff=
       F       F
Bank Sta=271,290.9
XS Rating Curve= 0 ,0
Exp/Cntr=0.3,0.1
LCMann Table=0

Chan Stop Cuts=-1
Use User Specified Reach Order=0
Composite Channel Slope=5